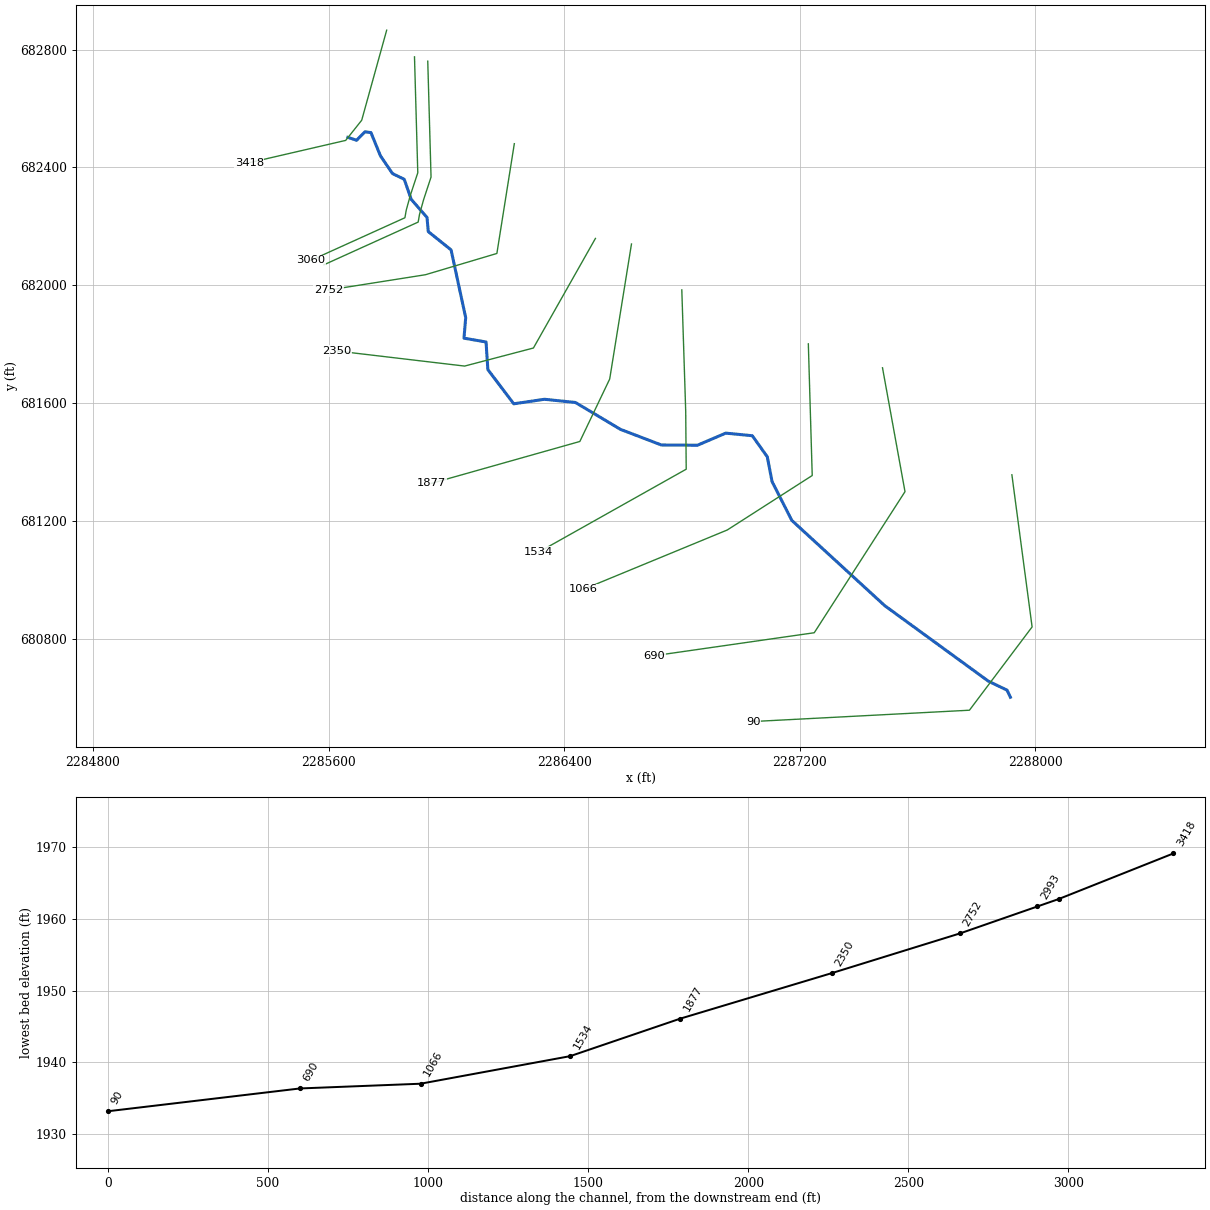
--- BEAVCK1T1.prj (project) ---

Proj Title=BEAVCK1T1
Current Plan=p01
Default Exp/Contr=0,0
English Units
Geom File=g01
Flow File=f01
Plan File=p01
BEGIN DESCRIPTION:
----------MODEL BY WOOD PLC 2022----------
AFH study
Randolph County, WV
HEC-RAS Version: RAS 6.2
Vertical Datum: NAVD88
Projection: NAD 1983 StatePlane West Virginia S FIPS 4702 (US Feet)
Terrain: 1-meter LIDAR (FEMA Region III 3DEP collected 2016-2018)
Land Use: 2019 NLCD
Hydrologic Method:
WV SIR2010-5033 regression equations
Additional Model Notes:
None
END DESCRIPTION:
DSS Export Rating Curves= 0
DSS Export Rating Curve Sorted= 0
DSS Export Volume Flow Curves= 0
DXF OffsetX= 0
DXF OffsetY= 0
DXF ScaleX= 0
DXF ScaleY= 0

--- BEAVCK1T1.p01 (plan) ---

Plan Title=Floodplain
Program Version=6.31
Short Identifier=Floodplain
Geom File=g01
Flow File=f01
Subcritical Flow
K Sum by GR= 0
Std Step Tol= 0.01
Critical Tol= 0.01
Num of Std Step Trials= 20
Max Error Tol= 0.3
Flow Tol Ratio= 0.001
Split Flow NTrial= 30
Split Flow Tol= 0.02
Split Flow Ratio= 0.02
Log Output Level= 0
Friction Slope Method= 1
Unsteady Friction Slope Method= 2
Unsteady Bridges Friction Slope Method= 1
Parabolic Critical Depth
Global Vel Dist= 0 , 0 , 0
Global Log Level= 0
CheckData=True
Encroach Param=-1 ,0,0, 0
Mapping Interval=1HOUR
Computation Time Step Use Courant=        0
Computation Time Step Use Time Series=    0
Computation Time Step Count To Double=0
Computation Time Step Max Doubling=0
Computation Time Step Max Halving=0
Computation Time Step Residence Courant=0
Run HTab= 0
Run UNet= 0
Run Sediment= 0
Run PostProcess= 0
Run WQNet= 0
Run RASMapper=-1
UNET Theta= 0
UNET Theta Warmup= 0
UNET ZTol= 0
UNET ZSATol= 0
UNET MxIter= 0
UNET Max Iter WO Improvement= 0
UNET MaxInSteps= 0
UNET DtIC= 0
UNET DtMin= 0
UNET MaxCRTS= 0
UNET WFStab= 0
UNET SFStab= 0
UNET WFX= 1
UNET SFX= 1
UNET Gravity=32.17405
UNET 1D Methodology=Finite Difference
UNET DSS MLevel= 1
UNET Pardiso=0
UNET DZMax Abort= 0
UNET Use Existing IB Tables= 0
UNET Froude Reduction=False
UNET Froude Limit= 0
UNET Froude Power= 0
UNET D1 Cores= 0
UNET WindReference=Eulerian
UNET WindDragFormulation=Hsu (1988)
UNET D2 Coriolis=0
UNET D2 Cores= 0
UNET D2 Theta= 1
UNET D2 Theta Warmup= 1
UNET D2 Z Tol= 0.01
UNET D2 Volume Tol= 0.01
UNET D2 Max Iterations= 20
UNET D2 Equation= 0
UNET D2 RampUpFraction=0.1
UNET D2 TimeSlices= 1
UNET D2 Turbulence Formulation=Non-Conservative (original)
UNET D2 Eddy Viscosity=0.3
UNET D2 Transverse Eddy Viscosity=0.1
UNET D2 Smagorinsky Mixing=0
UNET D2 BCVolumeCheck=0
UNET D2 Cores=0
UNET D2 SolverType=PARDISO (Direct)
UNET D2 Minimum Iterations= 3
UNET D2 Maximum Iterations= 30
UNET D2 Restart Number= 10
UNET D2 Relaxation Coeff=1.3
UNET D2 SOR Precondition Iterations= 10
UNET D2 ILUT Maximum Fill= 8
UNET D2 ILUT Tolerance=1E-08
UNET D2 Convergence Tolerance=0.00001
UNET D1D2 MaxIter= 0
UNET D1D2 ZTol=0.01
UNET D1D2 QTol=0.1
UNET D1D2 MinQTol=1
Write IC File= 0
Write IC File at Fixed DateTime=0
Write IC File at Sim End=0
Echo Input=False
Echo Parameters=False
Echo Output=False
Write Detailed= 0
HDF Write Warmup=0
HDF Write Time Slices=0
HDF Flush=0
HDF Compression= 1
HDF Chunk Size= 1
HDF Spatial Parts= 1
HDF Use Max Rows=0
HDF Fixed Rows= 1
Calibration Method= 0
Calibration Iterations= 20
Calibration Max Change=0.05
Calibration Tolerance=0.2
Calibration Maximum=1.5
Calibration Minimum=0.5
Calibration Optimization Method= 1
WQ AD Non Conservative
WQ ULTIMATE=-1
WQ Max Comp Step=1HOUR
WQ Output Interval=15MIN
WQ Output Selected Increments= 0
WQ Create Restart=0
WQ Fixed Restart=0
WQ System Summary=0
WQ Write To DSS=0
Sorting and Armoring Iterations= 10
XS Update Threshold= 0.02
Bed Roughness Predictor= 0
Hydraulics Update Threshold= 0.02
Energy Slope Method= 1
Volume Change Method= 1
Sediment Retention Method= 0
Sediment TS Multiplier= 1
Warm Up Method= 0
XS Weighting Method= 0
Number of US Weighted Cross Sections= 1
Number of DS Weighted Cross Sections= 1
Upstream XS Weight=0
Main XS Weight=1
Downstream XS Weight=0
Number of DS XS's Weighted with US Boundary= 1
Upstream Boundary Weight= 1
Weight of XSs Associated with US Boundary= 0
Number of US XS's Weighted with DS Boundary= 1
Downstream Boundary Weight= 0.5
Weight of XSs Associated with DS Boundary= 0.5
Percentile Method= 0
Sediment Output Level= 3
Mass or Volume Output= 0
Output Increment Type= 1
Profile and TS Output Increment= 1
Transport Output Increment 1
XS Output Flag= 0
XS Output Increment= 10
Read HDF5 Sediment Hotstart= 0
Sediment Hotstart Type= 0
Write Gradation File= 0
Read Gradation Hotstart= 0
Write HDF5 File= 1
Write Binary Output= 1
Write DSS Sediment File= 0
DSS Sediment Output Type= 1
SV Curve= 0
Specific Gage Flag= 0
Subcell Erosion Methods= 0
Subcell Deposition Methods= 0
Advection Scheme= 1
Matrix Solver= 0
Implicit Weighting Factor= 1
Maximum Outer Loop Convergence Iterations= 5
Convergence Maximum Absolute= 0.001
Convergence RMSE= 0.0001
Grain Fractions Max Abs Error= 0.001
Max Subgrid Regions= 1
Max Subgrid Length Scale= 3.402823E+38
Initial Layer Thickness= 3.402823E+38
Min Layer Thickness= 3.402823E+38
Max Layer Thickness= 3.402823E+38
Number of Layers= 5

--- BEAVCK1T1.f01 (steady flow) ---

Flow Title=Flow
Program Version=6.20
Number of Profiles= 1
Profile Names=P100yr
River Rch & RM=BEAVCK1T1,Main,3418
     230
Boundary for River Rch & Prof#=BEAVCK1T1,Main            , 1
Up Type= 0
Dn Type= 3
Dn Slope=0.00529
DSS Import GetInterval= 0
DSS Import GetPeak= 0
DSS Import FillOption= 0

--- BEAVCK1T1.g01 (geometry) ---

Geom Title=Geometry
Program Version=6.20

River Reach=BEAVCK1T1       ,Main
Reach XY= 30
2285665.36800002682501.7240000222285695.12345889682491.979855293
2285723.57173341682520.8094899592285743.92019872682517.864317349
2285776.20000003682438.8330000042285817.07809734682378.906298166
2285856.89576006682359.3878360512285880.57684883682291.371182685
2285934.15188115 682229.966883722285938.51767625682181.845296698
2286015.90600002682119.7399999952286065.53467074681889.664332327
     2286059.712681819.9810000062286134.66899998681807.101000011
2286140.79200001681713.3519999982286228.65904779681597.147913326
 2286332.9743842681612.545811217     2286438.098681601.665999994
2286591.15613648 681510.328901732286729.87000002681457.327000007
2286852.46818602 681456.458728942286948.59809957681497.583407315
2287038.65300003681488.7720000152287089.54871235681417.212815181
 2287105.7881233 681332.930958162287172.89071836681201.206116725
2287488.16600001680911.9310000092287839.73500001680655.729000002
2287903.65700004680624.798999995  2287915.074097680600.788092863

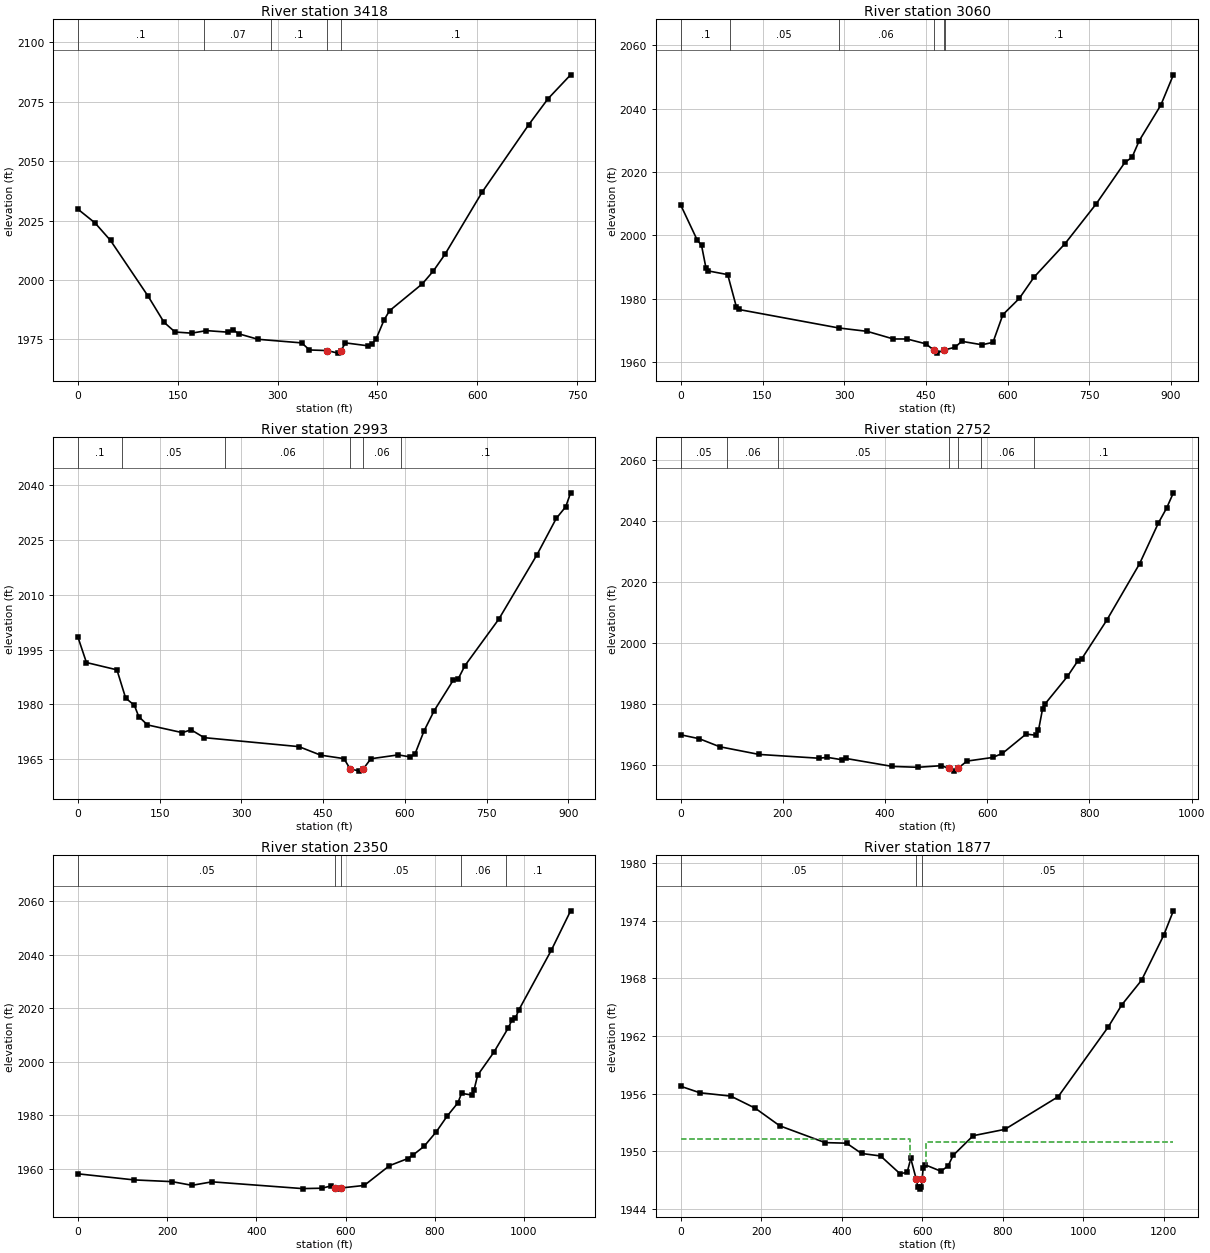
Type RM Length L Ch R = 1 ,3418    ,349.8,358.5,359
XS GIS Cut Line= 4
2285797.21442341682865.7092694852285712.44806819682559.975604506
2285658.07558351682491.5183459542285330.97634915682415.821490291
#Sta/Elev= 30
       0 2029.73    25.5 2023.99    48.8  2016.6   105.3 1993.13   129.2 1982.15
   145.8 1978.04   170.7 1977.56     193 1978.63   224.7 1977.99     233 1978.94
   241.8 1977.27   270.4 1974.98   336.2 1973.46   347.9 1970.48   374.71970.229
   390.6 1969.15  395.171970.226     402 1973.46   435.4 1972.25   441.6 1972.93
   448.2 1975.22     460 1983.13   468.2 1986.99   517.5 1998.33   533.9 2003.68
   551.6 2010.78   607.8 2037.12   677.6  2065.4   706.4 2076.27   740.4 2086.35
#Mann= 5 ,-1,0
       0      .1       0     190     .07       0     290      .1       0
   374.7    .045       0  395.17      .1       0
Bank Sta=374.7,395.17
XS Rating Curve= 0 ,0
Exp/Cntr=0.3,0.1

Type RM Length L Ch R = 1 ,3060    ,62.1,66.7,65.3
XS GIS Cut Line= 6
2285891.70280602682775.280040855 2285902.8548316682381.660864193
2285877.55371317682304.9413437932285863.67890629682254.747189488
2285859.13972345682228.8674410922285539.11441184682083.882688347
#Sta/Elev= 30
       0 2009.52    30.1 1998.52    38.1  1996.8    46.1 1989.77    50.1 1988.76
    86.1 1987.59   102.1 1977.33   106.1 1976.58     290 1970.73   342.2 1969.66
   390.3 1967.25   415.3 1967.25     450 1965.71  464.541963.714   470.1 1962.78
  482.311963.715   503.4 1964.63   515.8 1966.51   552.9 1965.42   573.1 1966.18
   591.3 1974.93   621.4 1980.06   648.4 1986.76   705.5 1997.39   762.6 2009.93
   815.3 2023.04   828.4 2024.64   841.6  2029.9   881.3 2041.15   904.3 2050.71
#Mann= 6 ,-1,0
       0      .1       0      90     .05       0     290     .06       0
  464.54    .045       0  482.31     .06       0  484.56      .1       0
Bank Sta=464.54,482.31
XS Rating Curve= 0 ,0
Exp/Cntr=0.3,0.1

Type RM Length L Ch R = 1 ,2993    ,247.8,241.1,226.5
XS GIS Cut Line= 6
 2285936.7234366682760.5475588672285947.87546218682366.928382206
2285922.57434375682290.2088618052285908.69953687682240.014707501
2285904.16035402682214.1349591042285584.13504241 682069.15020636
#Sta/Elev= 30
       0 1998.35    15.4 1991.48    71.4 1989.48    87.4 1981.75   103.4 1979.77
   111.4 1976.68   127.4  1974.4   191.4 1972.28   207.5 1973.06   231.5 1970.91
   405.5 1968.45   445.5 1966.11   488.1 1965.17  499.391962.399   516.3 1961.74
  523.94  1962.4   537.6 1965.13     588 1966.19     610 1965.62   618.8 1966.51
   635.2 1972.75   653.9 1978.31     689 1986.68   697.8 1986.98   710.3 1990.63
   772.5 2003.37   842.7 2021.04   877.9 2030.94   895.4 2034.16   904.3 2037.96
#Mann= 6 ,-1,0
       0      .1       0      80     .05       0     270     .06       0
  499.39    .045       0  523.94     .06       0  592.92      .1       0
Bank Sta=499.39,523.94
XS Rating Curve= 0 ,0
Exp/Cntr=0.3,0.1

Type RM Length L Ch R = 1 ,2752    ,396.5,401.7,395.5
XS GIS Cut Line= 4
2286230.65270762682480.4107408442286171.41179048682107.626432996
2285928.66852026682035.3814120952285599.23122495681983.364997046
#Sta/Elev= 30
       0 1969.91    36.4 1968.61    76.2 1965.99   153.1 1963.47   270.6 1962.22
   286.8 1962.51   315.1 1961.73   323.2 1962.15   414.1 1959.53   464.3 1959.25
   510.2 1959.78  524.261958.906   535.3 1957.99  542.381958.906   560.3 1961.29
   610.4 1962.47   629.7 1963.82   675.8 1970.14     696 1969.75   700.1 1971.33
   708.2 1978.45   712.2 1979.87   756.8 1989.05     777 1994.11   785.1 1994.91
   833.7 2007.48     898 2026.01   934.9 2039.41   950.9 2044.26   964.2  2049.3
#Mann= 7 ,-1,0
       0     .05       0      90     .06       0     190     .05       0
  524.26    .045       0  542.38     .05       0  587.46     .06       0
  690.73      .1       0
Bank Sta=524.26,542.38
XS Rating Curve= 0 ,0
Exp/Cntr(USF)=0,0
Exp/Cntr=0.3,0.1

Type RM Length L Ch R = 1 ,2350    ,467.1,473,476.2
XS GIS Cut Line= 4
2286506.01670125682158.6828217372286295.47871978681786.577704329
2286061.94935555681725.2801566082285629.17566363681776.356183185
#Sta/Elev= 30
       0 1958.15   125.6 1955.88   210.9 1955.23   255.5 1953.85   300.5 1955.16
   503.5 1952.63   546.7 1952.77   567.4 1953.62  576.521952.852   582.1 1952.43
  589.241952.849   641.9 1953.81   698.5  1961.2   739.6 1963.86   751.3 1965.18
   776.2 1968.44   803.6 1973.88   827.8 1979.71     852 1984.69   860.1 1988.23
   884.2 1987.59   888.3 1989.57   896.3 1995.03   932.6 2003.59   964.8 2012.65
   972.8 2015.47   980.9 2016.36     989 2019.52  1061.5 2041.73  1104.8 2056.47
#Mann= 5 ,-1,0
       0     .05       0  576.52    .045       0  589.24     .05       0
  858.98     .06       0  958.98      .1       0
Bank Sta=576.52,589.24
XS Rating Curve= 0 ,0
Exp/Cntr=0.3,0.1

Type RM Length L Ch R = 1 ,1877    ,339.6,343.5,344.6
XS GIS Cut Line= 4
2286628.43886892  682139.73293582286554.49987046681681.319168155
2286453.10965691 681469.252525832285948.85577695681326.872833978
#Sta/Elev= 30
       0 1956.78    47.2 1956.11   124.1 1955.76   184.9  1954.5   245.7 1952.67
   358.3 1950.92   411.8 1950.86     449 1949.79   496.2 1949.53   544.3 1947.69
   562.2 1947.82   571.2 1949.27  584.821947.104   588.6 1946.35   593.1 1946.08
   597.5 1946.32  599.351947.104   601.9 1948.25   606.4 1948.62   646.2 1947.94
     664  1948.5   676.2 1949.58   726.1 1951.64   804.9  1952.3   937.3  1955.7
    1062 1962.98  1095.2 1965.25  1144.3 1967.81  1199.4  1972.5  1223.4 1975.04
#Mann= 3 ,-1,0
       0     .05       0  584.82    .045       0  599.35     .05       0
#XS Ineff= 2 , 0
          568.74 1951.31  609.09         1950.99
Permanent Ineff=
       F       F
Bank Sta=584.82,599.35
XS Rating Curve= 0 ,0
Exp/Cntr=0.3,0.1

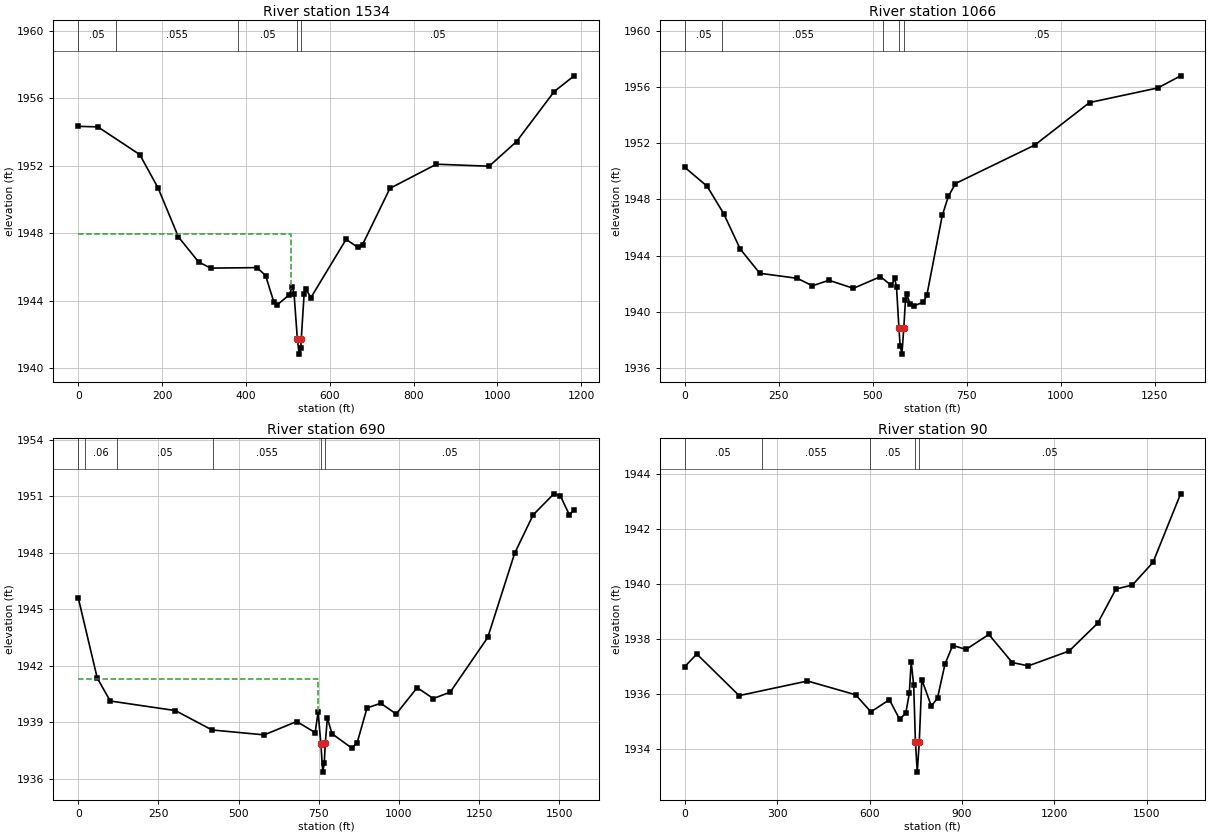
Type RM Length L Ch R = 1 ,1534    ,472.5,467.5,461.3
XS GIS Cut Line= 4
2286799.33258845681983.921312794 2286812.5885072681570.991265986
2286814.26306196 681375.082564052286313.82244988681093.837383828
#Sta/Elev= 30
       0 1954.33    46.8  1954.3   146.8 1952.66   190.8 1950.67   238.9 1947.79
   287.3  1946.3   316.2 1945.94   426.4 1945.97     447  1945.5     467 1943.91
     475 1943.77     503 1944.35     511 1944.84     515 1944.38  522.741941.768
     527 1940.85     531 1941.19  532.151941.765     539 1944.43     543 1944.71
     555 1944.19     639 1947.64   666.5 1947.18   678.3 1947.33   743.6 1950.66
   854.6 1952.09   980.3 1951.97  1045.7 1953.43  1135.5 1956.39  1183.1 1957.32
#Mann= 5 ,-1,0
       0     .05       0      90    .055       0     380     .05       0
  522.74    .045       0  532.15     .05       0
#XS Ineff= 2 , 0
          508.59 1947.93
Permanent Ineff=
       F       F
Bank Sta=522.74,532.15
XS Rating Curve= 0 ,0
Exp/Cntr=0.3,0.1

Type RM Length L Ch R = 1 ,1066    ,371.8,376.6,377.8
XS GIS Cut Line= 4
2287228.92904247681800.7430063832287242.14258081681353.684959046
2286953.64699361681168.6954222172286464.25668454680966.821919725
#Sta/Elev= 30
       0 1950.29    59.6 1948.94   103.6    1947   147.6 1944.48   199.7 1942.75
   299.7 1942.39   339.7 1941.86   383.8 1942.25     449 1941.68   520.9 1942.51
   549.4 1941.89   558.9 1942.38   563.6 1941.75  569.991938.854   573.1 1937.61
   577.9    1937  582.951938.855   587.4 1940.86   590.9 1941.31   599.6 1940.53
     611 1940.44   634.9  1940.7   644.4 1941.21   685.3 1946.86   701.4 1948.21
   720.4 1949.13   931.6 1951.87  1077.1 1954.89  1258.9 1955.93  1319.4 1956.79
#Mann= 5 ,-1,0
       0     .05       0     100    .055       0  527.25     .05       0
  569.99    .045       0  582.95     .05       0
Bank Sta=569.99,582.95
XS Rating Curve= 0 ,0
Exp/Cntr(USF)=0,0
Exp/Cntr=0.3,0.1

Type RM Length L Ch R = 1 ,690     ,599.7,599.6,598.9
XS GIS Cut Line= 4
2287480.75954548681719.4956243422287557.15908228681298.932080806
2287249.06830711680819.8728011612286705.61967261680741.802540223
#Sta/Elev= 30
       0 1945.61    59.3 1941.34    99.9 1940.12   303.2 1939.61     417 1938.58
   579.9 1938.32   681.2 1939.03   738.7 1938.44   747.8 1939.54  756.461937.851
   762.4 1936.34   767.2 1936.85   770.21937.867   776.7 1939.21   791.2 1938.38
   852.8 1937.62   869.4 1937.89   900.4 1939.75   943.2    1940   991.3 1939.43
  1056.7 1940.83    1107 1940.25  1159.6 1940.59  1276.8  1943.5  1360.6 1947.97
  1418.2 1950.01  1482.9 1951.13  1503.1 1951.02  1531.3 1950.01  1546.1 1950.27
#Mann= 6 ,-1,0
       0     .05       0      20     .06       0     120     .05       0
     420    .055       0  756.46    .045       0   770.2     .05       0
#XS Ineff= 2 , 0
          747.44  1941.3
Permanent Ineff=
       F       F
Bank Sta=756.46,770.2
XS Rating Curve= 0 ,0
Exp/Cntr(USF)=0,0
Exp/Cntr=0.3,0.1

Type RM Length L Ch R = 1 ,90      ,,,
XS GIS Cut Line= 4
2287920.06891292681356.2103225792287988.71669482680839.555908106
2287775.92389128680556.7696706032287042.69341702680518.407465403
#Sta/Elev= 30
       0 1936.99    39.4 1937.45   176.6 1935.94   398.5 1936.47   554.7 1935.97
   604.3 1935.35   664.3 1935.79   697.5 1935.08   717.5  1935.3   728.9 1936.02
     735 1937.17   743.2 1936.31  748.79 1934.25   754.7 1933.16  761.171934.249
   769.5 1936.52   800.4 1935.56   820.4 1935.85   844.6 1937.08   869.6 1937.76
   913.3 1937.62     987 1938.16  1063.1 1937.14  1115.2 1937.02  1247.5 1937.56
  1340.2 1938.57  1399.4 1939.81    1453 1939.96  1519.7 1940.78  1609.3 1943.27
#Mann= 5 ,-1,0
       0     .05       0     250    .055       0   601.2     .05       0
  748.79    .045       0  761.17     .05       0
Bank Sta=748.79,761.17
XS Rating Curve= 0 ,0
Exp/Cntr(USF)=0,0
Exp/Cntr=0.3,0.1
LCMann Table=0

Chan Stop Cuts=-1
Use User Specified Reach Order=0
Composite Channel Slope=5